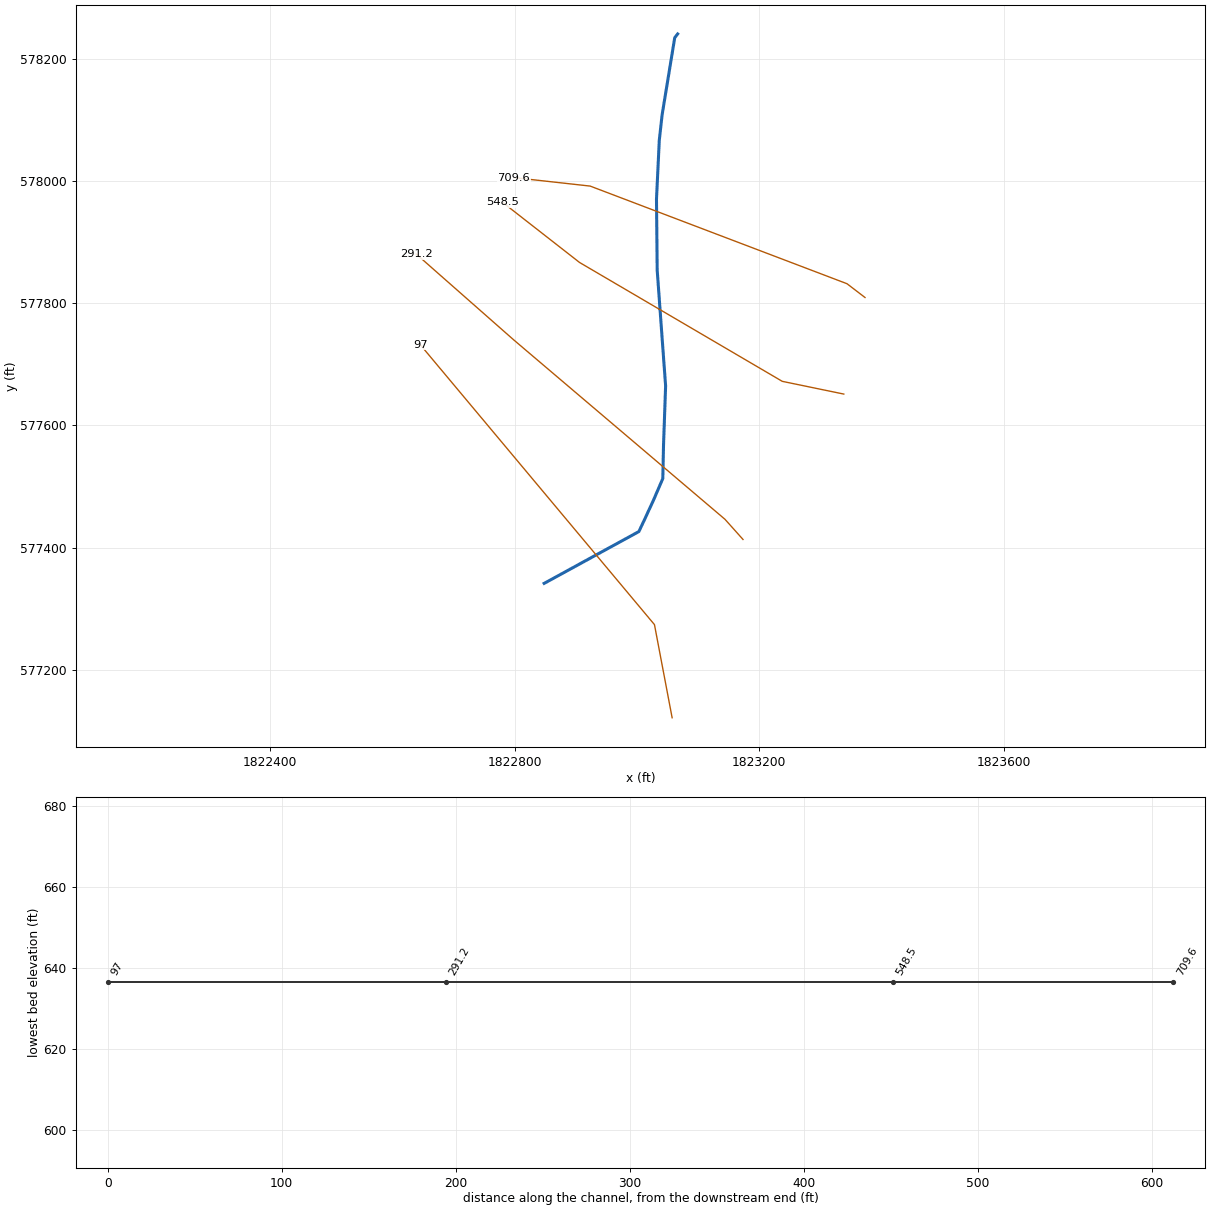
--- POCATALRIV.prj (project) ---

Proj Title=POCATALRIV
Current Plan=p01
Default Exp/Contr=0,0
English Units
Geom File=g01
Flow File=f01
Plan File=p01
BEGIN DESCRIPTION:
END DESCRIPTION:
DSS Export Rating Curves= 0
DSS Export Rating Curve Sorted= 0
DSS Export Volume Flow Curves= 0
DXF OffsetX= 0
DXF OffsetY= 0
DXF ScaleX= 0
DXF ScaleY= 0

--- POCATALRIV.p01 (plan) ---

Plan Title=Floodplain
Program Version=4.00
Geom File=g01
Flow File=f01
K Sum by GR=0
Std Step Tol=0.01
Critical Tol=0.01
Num of Std Step Trials=20
Max Error Tol=0.3
Flow Tol Ratio=0.001
Split Flow NTrial=30
Split Flow Tol=0.02
Split Flow Ratio=0.02
Log Output Level=0
Friction Slope Method=1
Unsteady Friction Slope Method=2
Unsteady Bridges Friction Slope Method=1
Global Log Level=0
CheckData=False
Run HTab=0
Run UNet=0
Run PostProcess=0
UNET Theta=0
UNET Theta Warmup=0
UNET ZTol=0
UNET ZSATol=0
UNET MxIter=0
UNET MaxInSteps=0
UNET DtIC=0
UNET DtMin=0
UNET MaxCRTS=0
UNET WFStab=0
UNET SFStab=0
UNET WFX=0
UNET SFX=0
UNET DSS MLevel=0
UNET DZMax Abort=0
UNET Convert EG Bridges=0
UNET Use Existing IB Tables=0
UNET Froude Limit=0
UNET Froude Power=0
Write IC File=0
Echo Input=False
Echo Output=False
Write Detailed=0

--- POCATALRIV.f01 (steady flow) ---

Flow Title=NFF Regression Equation
Program Version=4.10
Number of Profiles= 1
Profile Names=P100yr
River Rch & RM=POCATALRIV,Main            ,709.6
14327.19
River Rch & RM=POCATALRIV,Main            ,548.5
14359.55
Boundary for River Rch & Prof#=POCATALRIV,Main            , 1
Up Type= 0
Dn Type= 1
Dn Known WS=671.8
DSS Import GetInterval= 0
DSS Import GetPeak= 0
DSS Import FillOption= 0

--- POCATALRIV.g01 (geometry) ---

Geom Title=USGS 10m DEM
Program Version=4.10

River Reach=POCATALRIV      ,Main
Reach XY= 15
      1823066.42      578240.456     1823061.645      578234.386
     1823040.968      578108.028     1823036.373      578066.674
     1823031.778      577970.183     1823032.416      577905.782
     1823032.927      577854.163     1823039.819       577758.82
     1823046.711      577664.626     1823043.265      577566.985
     1823042.117      577512.996     1823026.613      577477.124
     1823012.433        577446.4     1823002.979      577426.311
     1822847.991      577341.526

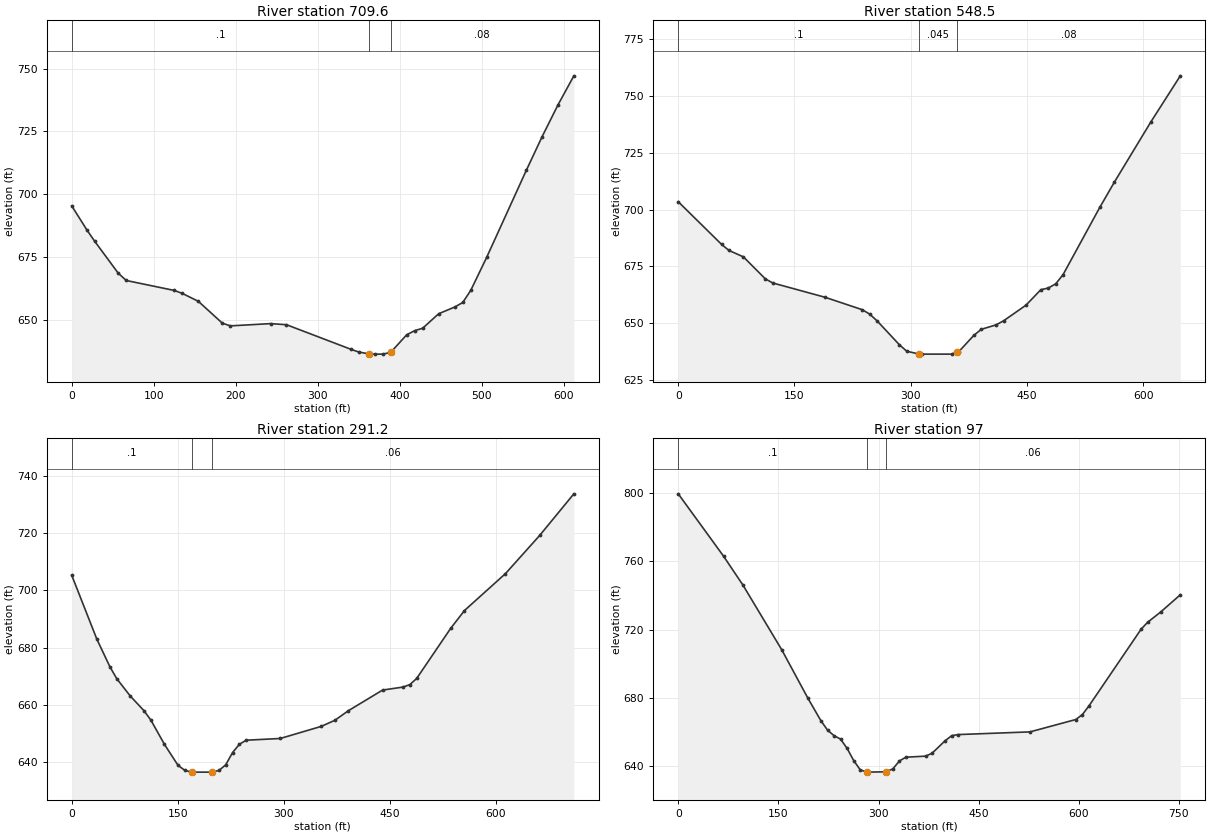
Type RM Length L Ch R = 1 ,709.6   ,166.4,161.1,155.8
XS GIS Cut Line= 4
      1823372.98      577809.248     1823343.467      577831.818
     1822923.328       577991.54     1822798.328      578005.429
#Sta/Elev= 30
       0   695.4    18.6  685.76    27.9  681.38    56.7  668.65    66.5  665.76
   125.1   661.8   134.9  660.62   154.4  657.48   183.7  648.79   193.5  647.73
   242.4  648.62   261.9  648.19   340.1  638.47   349.8  637.36   362.9  636.57
   369.4   636.5   379.2   636.5   388.9  637.16   408.5  644.18   418.2  645.82
     428  646.79   447.5  652.55   467.1  655.21   476.9  657.02   486.6   661.8
     506   674.9   554.4  709.52   573.7  722.92     593  735.51   612.4  747.09
#Mann= 3 , 0 , 0
       0      .1       0   362.9    .045       0   388.9     .08       0
Bank Sta=362.9,388.9
XS Rating Curve= 0 ,0
Exp/Cntr=0.3,0.1

Type RM Length L Ch R = 1 ,548.5   ,262.2,257.3,252.7
XS GIS Cut Line= 4
     1823338.258      577651.262     1823237.564      577672.095
     1822905.967       577866.54      1822779.23      577965.498
#Sta/Elev= 30
       0  703.46    56.1  684.67    65.4  682.07    84.1  679.23   112.4  669.57
     122  667.76   189.3   661.5   237.4  656.03     247  654.11   256.6  651.13
   285.4  640.63     295  637.76   310.2   636.6   314.2   636.5   352.7   636.5
     360 637.375   362.3  637.65   381.5  644.74   391.1   647.4   410.4  649.37
     420  651.16   448.8     658     468  664.81   477.6  665.53   487.2   667.4
   496.7  671.43     544  700.93   562.9  712.07   610.2  738.64     648  758.77
#Mann= 3 , 0 , 0
       0      .1       0   310.2    .045       0     360     .08       0
Bank Sta=310.2,360
XS Rating Curve= 0 ,0
Exp/Cntr=0.3,0.1

Type RM Length L Ch R = 1 ,291.2   ,195.7,194.2,192.5
XS GIS Cut Line= 4
     1823173.328      577413.415     1823143.814      577446.401
     1822798.328      577739.804     1822638.605      577880.429
#Sta/Elev= 30
       0  705.25    35.4  683.01    53.9  673.33    63.6  669.17    82.8  663.08
   102.1  657.98   111.8  654.72   131.1  646.21   150.3  638.88     160  637.11
   169.6   636.5   198.6   636.5   208.2  637.08   217.8  639.06   227.5  643.34
   237.1  646.23   246.8  647.65     295  648.26   352.9  652.48   372.2  654.61
   391.4  657.97   439.7  665.17   468.6  666.22   478.2  667.07   487.9  669.22
   536.2  686.79   555.6  692.97   613.6  705.87     662  719.21   710.3  733.74
#Mann= 3 , 0 , 0
       0      .1       0   169.6    .045       0   198.6     .06       0
Bank Sta=169.6,198.6
XS Rating Curve= 0 ,0
Exp/Cntr=0.3,0.1

Type RM Length L Ch R = 1 ,97      ,101.4,97,92.5
XS GIS Cut Line= 3
      1823057.38       577121.68     1823028.459      577274.058
     1822645.373       577731.93
#Sta/Elev= 30
       0  799.55    67.9  763.01    96.9  746.11   155.1  708.16   194.2  679.83
   213.8  666.57   223.6  661.15   233.4  657.86   243.2  655.84     253  650.39
   262.8  643.31   272.5   637.9   282.3   636.5   311.2  636.69   321.5  638.41
   331.3  643.04     341  645.25   370.4  645.86   380.2  647.54   399.8   654.9
   409.6  657.85   419.3   658.5     527  660.08   595.5  667.32   605.3  670.16
   615.1  675.21   693.4  720.26   703.2  724.31   722.7  730.32   752.1   740.4
#Mann= 3 , 0 , 0
       0      .1       0   282.3    .045       0   311.2     .06       0
Bank Sta=282.3,311.2
XS Rating Curve= 0 ,0
Exp/Cntr=0.3,0.1

Chan Stop Cuts=-1
Use User Specified Reach Order=0
Composite Channel Slope=5